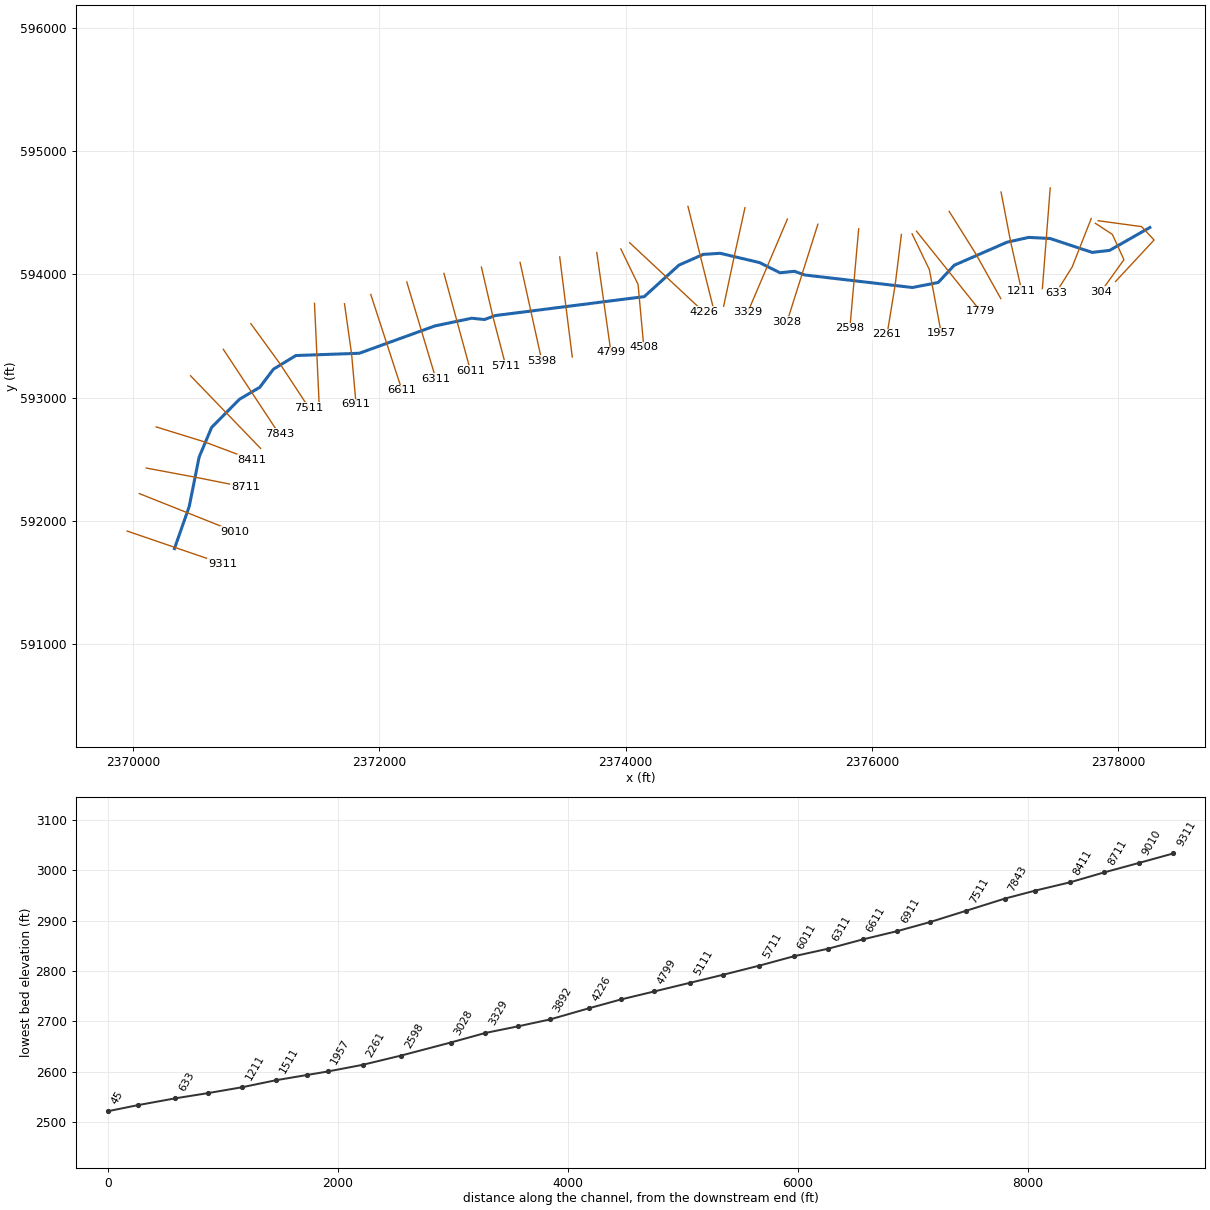
--- TEETERCRN.prj (project) ---

Proj Title=TEETERCRN
Current Plan=p01
Default Exp/Contr=0,0
English Units
Geom File=g01
Flow File=f01
Plan File=p01
BEGIN DESCRIPTION:
Stream Name:Teeter Camp Run
Flood Zone: Approximate
Pendleton County, West Virginia
HEC-RAS Version: 5.0.7
Hydrology Method:
Regression equation
END DESCRIPTION:
DSS File=dss
DSS Export Rating Curves= 0
DSS Export Rating Curve Sorted= 0
DSS Export Volume Flow Curves= 0
DXF OffsetX= 0
DXF OffsetY= 0
DXF ScaleX= 0
DXF ScaleY= 0

--- TEETERCRN.p01 (plan) ---

Plan Title=Floodplain
Program Version=5.07
Short Identifier=Floodplain
Geom File=g01
Flow File=f01
Subcritical Flow
K Sum by GR= 0
Std Step Tol= 0.01
Critical Tol= 0.01
Num of Std Step Trials= 20
Max Error Tol= 0.3
Flow Tol Ratio= 0.001
Split Flow NTrial= 30
Split Flow Tol= 0.02
Split Flow Ratio= 0.02
Log Output Level= 0
Friction Slope Method= 1
Unsteady Friction Slope Method= 2
Unsteady Bridges Friction Slope Method= 1
Parabolic Critical Depth
Global Vel Dist= 0 , 0 , 0
Global Log Level= 0
CheckData=True
Encroach Param=-1 ,0,0, 0
Computation Interval=0.1SEC
Output Interval=1MIN
Instantaneous Interval=Max Profile
Mapping Interval=1HOUR
Computation Time Step Use Courant=        0
Computation Time Step Use Time Series=    0
Computation Time Step Count To Double=0
Computation Time Step Max Doubling=0
Computation Time Step Max Halving=0
Computation Time Step Residence Courant=0
Run HTab= 0
Run UNet= 0
Run Sediment= 0
Run PostProcess= 0
Run WQNet= 0
Run RASMapper= 0
UNET Theta= 0
UNET Theta Warmup= 0
UNET ZTol= 0
UNET ZSATol= 0
UNET MxIter= 0
UNET Max Iter WO Improvement= 0
UNET MaxInSteps= 0
UNET DtIC= 0
UNET DtMin= 0
UNET MaxCRTS= 0
UNET WFStab= 0
UNET SFStab= 0
UNET WFX= 1
UNET SFX= 1
UNET 1D Methodology=Finite Difference
UNET DSS MLevel= 1
UNET Pardiso=0
UNET DZMax Abort= 0
UNET Use Existing IB Tables= 0
UNET Froude Reduction=False
UNET Froude Limit= 0
UNET Froude Power= 0
UNET D1 Cores= 0
UNET D2 Coriolis=0
UNET D2 Cores= 0
UNET D2 Theta= 1
UNET D2 Theta Warmup= 1
UNET D2 Z Tol= 0.01
UNET D2 Volume Tol= 0.01
UNET D2 Max Iterations= 20
UNET D2 Equation= 0
UNET D2 RampUpFraction=0.1
UNET D2 TimeSlices= 1
UNET D2 BCVolumeCheck=0
UNET D1D2 MaxIter= 0
UNET D1D2 ZTol=0.01
UNET D1D2 QTol=0.1
UNET D1D2 MinQTol=1
DSS File=dss
Write IC File= 0
Write IC File at Fixed DateTime=0
Write IC File at Sim End=0
Echo Input=False
Echo Parameters=False
Echo Output=False
Write Detailed= 0
HDF Write Warmup=0
HDF Write Time Slices=0
HDF Flush=0
HDF Face Node Velocities=0
HDF Compression= 1
HDF Chunk Size= 1
HDF Spatial Parts= 1
HDF Use Max Rows=0
HDF Fixed Rows= 1
Calibration Method= 0
Calibration Iterations= 20
Calibration Max Change=0.05
Calibration Tolerance=0.2
Calibration Maximum=1.5
Calibration Minimum=0.5
Calibration Optimization Method= 1
WQ AD Non Conservative
WQ ULTIMATE=-1
WQ Max Comp Step=1HOUR
WQ Output Interval=15MIN
WQ Output Selected Increments= 0
WQ Output face flow=0
WQ Output face velocity=0
WQ Output face area=0
WQ Output face dispersion=0
WQ Output cell volume=0
WQ Output cell surface area=0
WQ Output cell continuity=0
WQ Output cumulative cell continuity=0
WQ Output face conc=0
WQ Output face dconc_dx=0
WQ Output face courant=0
WQ Output face peclet=0
WQ Output face adv mass=0
WQ Output face disp mass=0
WQ Output cell mass=0
WQ Output cell source sink temp=0
WQ Output nsm pathways=0
WQ Output nsm derived pathways=0
WQ Output MaxMinRange=-1
WQ Daily Max Min Mean=-1
WQ Daily Range=0
WQ Daily Time=0
WQ Create Restart=0
WQ Fixed Restart=0
WQ System Summary=0
WQ Write To DSS=0
WQ Use Fixed Temperature=0
Sorting and Armoring Iterations= 10
XS Update Threshold= 0.02
Bed Roughness Predictor= 0
Hydraulics Update Threshold= 0.02
Energy Slope Method= 1
Volume Change Method= 1
Sediment Retention Method= 0
XS Weighting Method= 0
Number of US Weighted Cross Sections= 1
Number of DS Weighted Cross Sections= 1
Upstream XS Weight=0
Main XS Weight=1
Downstream XS Weight=0
Number of DS XS's Weighted with US Boundary= 1
Upstream Boundary Weight= 1
Weight of XSs Associated with US Boundary= 0
Number of US XS's Weighted with DS Boundary= 1
Downstream Boundary Weight= 0.5
Weight of XSs Associated with DS Boundary= 0.5
Percentile Method= 0
Sediment Output Level= 3
Mass or Volume Output= 0
Output Increment Type= 1
Profile and TS Output Increment= 1
XS Output Flag= 0
XS Output Increment= 10
Write Gradation File= 0
Read Gradation Hotstart= 0
Write HDF5 File= 1
Write Binary Output= 1
Write DSS Sediment File= 0
SV Curve= 0
Specific Gage Flag= 0

--- TEETERCRN.f01 (steady flow) ---

Flow Title=Flows
Program Version=5.07
Number of Profiles= 6
Profile Names=P100yr,P10yr,P25yr,P50yr,P500yr,P101yr
River Rch & RM=TEETERCRN,Main            ,9311
     447     210     296     369     653     544
River Rch & RM=TEETERCRN,Main            ,8711
     617     288     408     509     905     751
River Rch & RM=TEETERCRN,Main            ,7194
     851     396     561     702    1252    1036
River Rch & RM=TEETERCRN,Main            ,2598
    1385     639     909    1140    2049    1685
Boundary for River Rch & Prof#=TEETERCRN,Main            , 1
Up Type= 0
Dn Type= 3
Dn Slope=0.04636
Boundary for River Rch & Prof#=TEETERCRN,Main            , 2
Up Type= 0
Dn Type= 3
Dn Slope=0.04636
Boundary for River Rch & Prof#=TEETERCRN,Main            , 3
Up Type= 0
Dn Type= 3
Dn Slope=0.04636
Boundary for River Rch & Prof#=TEETERCRN,Main            , 4
Up Type= 0
Dn Type= 3
Dn Slope=0.04636
Boundary for River Rch & Prof#=TEETERCRN,Main            , 5
Up Type= 0
Dn Type= 3
Dn Slope=0.04636
Boundary for River Rch & Prof#=TEETERCRN,Main            , 6
Up Type= 0
Dn Type= 3
Dn Slope=0.04636
DSS Import GetInterval= 0
DSS Import GetPeak= 0
DSS Import FillOption= 0

--- TEETERCRN.g01 (geometry) ---

Geom Title=Geometry
Program Version=5.07

River Reach=TEETERCRN       ,Main
Reach XY= 30
2370337.92600003591775.4019999952370457.77500001592117.383000016
     2370538.111592517.8410000062370639.59100002592758.963000014
2370865.95700002592987.6449999962371030.61800003593084.499000013
2371141.08400002593231.2539999932371323.31000003593342.281000003
2371838.19999999593360.6130000052372451.35400003593582.360000014
      2372750.25593644.931999996     2372853.551593634.438000008
     2372939.574593666.231000006     2374151.042593820.421000004
2374432.91600004594076.290999994     2374630.289594163.258000016
2374767.73300004594171.9970000092375086.65799999594096.873000011
2375252.93000001594014.0649999982375370.35800004594025.952000007
     2375453.741 593996.054000022376326.91200003593894.324000001
2376536.88700002593935.039000005     2376667.294594075.187999994
2377094.82200003594261.8050000072377271.70100003 594301.13000001
2377445.45500004594292.2269999982377786.26000002594179.262000009
2377927.49000001594195.4410000152378254.53810337 594381.14160423

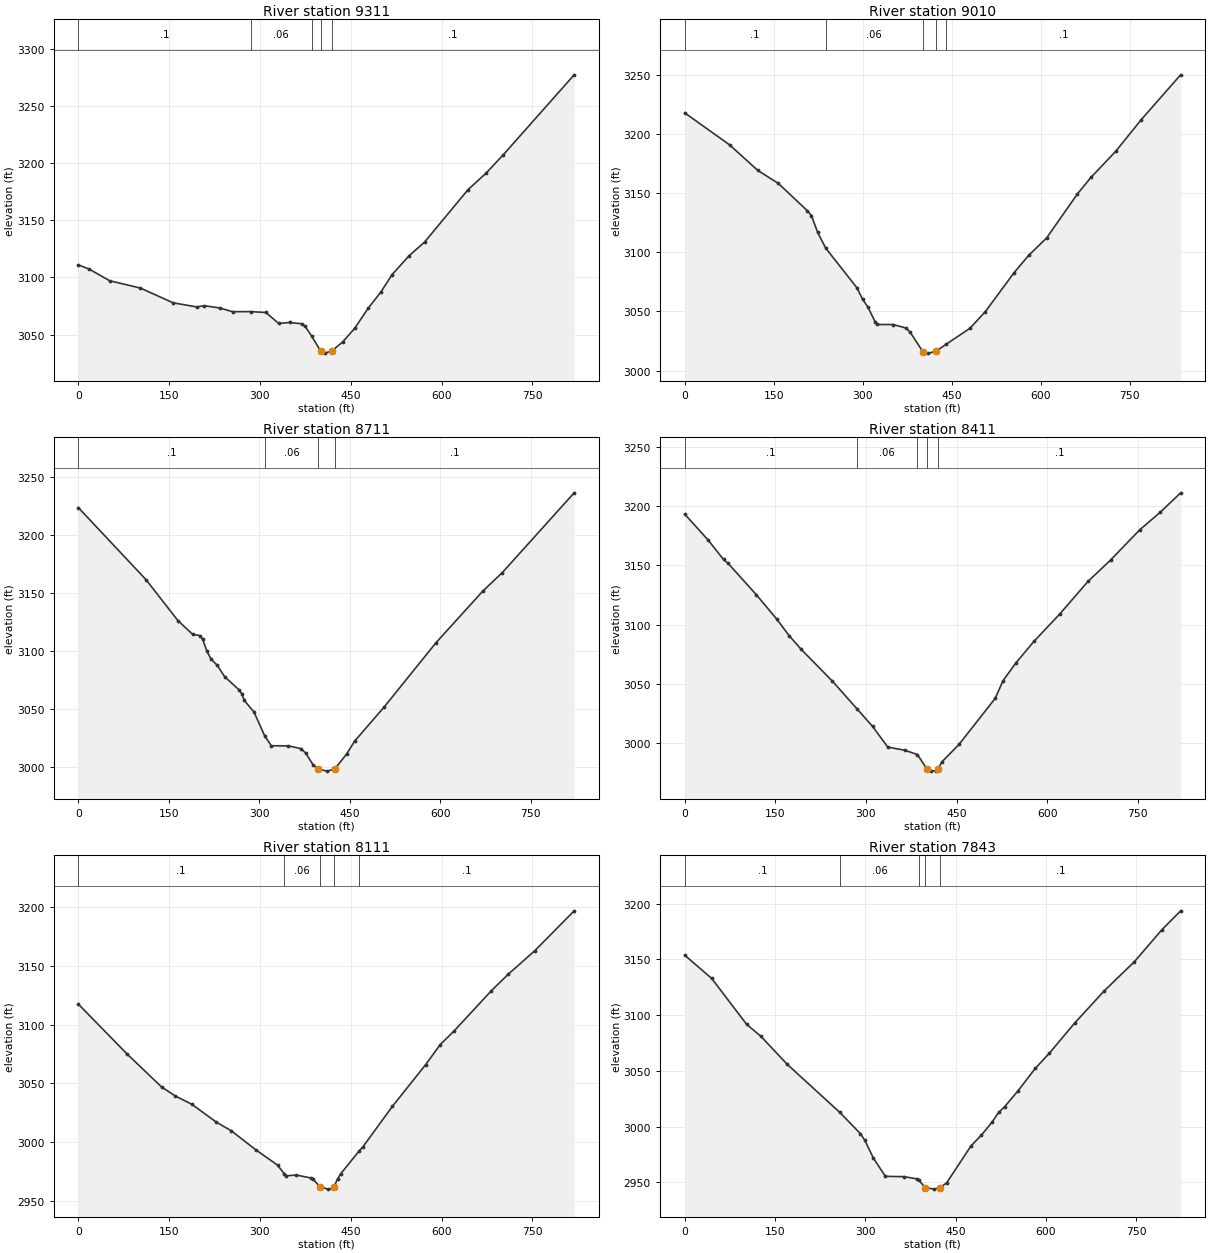
Type RM Length L Ch R = 1 ,9311    ,301.7,301.2,300
XS GIS Cut Line= 3
     2369953.782      591917.611     2370341.168      591784.862
     2370728.554      591652.114
#Sta/Elev= 30
       0 3111.05    17.9 3107.35    51.8 3097.11   102.5 3090.73   156.5 3077.82
   195.5 3074.24   208.2 3075.28   233.6 3073.31   254.7 3070.04  284.443070.132
   309.7 3069.37   330.8 3059.81   349.3  3060.6   368.9 3059.46   374.5  3057.3
   385.23048.873  400.37 3035.49   406.9 3033.79   418.6 3035.69   436.5 3043.51
   456.4 3055.42   478.8 3073.11     500 3087.46   518.2 3102.48   546.5 3119.11
   571.8  3130.9   643.7 3176.85   673.7 3191.39     702  3207.4     819 3277.33
#Mann= 5 ,-1 , 0
       0      .1       0  284.44     .06       0   385.2      .1       0
  400.37    .045       0   418.6      .1       0
Bank Sta=400.37,418.6
XS Rating Curve= 0 ,0
Exp/Cntr=0.3,0.1

Type RM Length L Ch R = 1 ,9010    ,295.1,298.8,301.2
XS GIS Cut Line= 2
     2370052.496      592221.8062370828.42689034591912.324697128
#Sta/Elev= 30
       0 3217.87    75.6 3190.81     123 3169.25   157.5  3158.3   206.6 3135.12
   213.4 3131.04   223.8  3116.9  237.283103.654   290.3 3069.83   299.5 3060.29
   308.2 3053.99   321.1 3040.81   324.1 3038.99   351.2 3038.94   372.8 3035.98
   379.6 3032.53   401.1 3016.03   410.3 3014.78   422.7 3016.17  440.76 3022.44
   480.4 3035.74   506.3 3049.82     555 3082.93   579.7  3097.6   609.6 3112.13
   661.3 3149.22   684.3 3163.33   725.9 3185.33     769 3212.13   835.4 3250.06
#Mann= 5 ,-1 , 0
       0      .1       0  237.28     .06       0   401.1    .045       0
   422.7     .06       0  440.76      .1       0
Bank Sta=401.1,422.7
XS Rating Curve= 0 ,0
Exp/Cntr=0.3,0.1

Type RM Length L Ch R = 1 ,8711    ,301.3,300,296.8
XS GIS Cut Line= 3
     2370108.342      592429.193     2370514.161      592353.206
     2370915.489      592273.157
#Sta/Elev= 30
       0 3223.83   112.3 3161.54   165.2 3126.18   189.6 3114.33   201.9 3113.27
   206.3 3109.91   213.1 3099.88     220 3093.01   230.3 3087.66   242.5 3077.85
     267 3066.13     271 3063.07   275.1 3057.32   291.4 3047.09   309.1 3026.55
   319.9 3018.13   348.4 3017.99   368.7 3015.69   376.8 3011.94     389 3001.83
   398.2 2997.89   412.9  2996.2   425.5 2998.21   445.2 3011.27   458.3 3022.21
   507.2 3051.66   592.9 3107.04   670.4 3151.57   703.1 3167.76   822.1 3236.58
#Mann= 4 ,-1 , 0
       0      .1       0   309.1     .06       0   398.2    .045       0
   425.5      .1       0
Bank Sta=398.2,425.5
XS Rating Curve= 0 ,0
Exp/Cntr=0.3,0.1

Type RM Length L Ch R = 1 ,8411    ,306.8,300,292.5
XS GIS Cut Line= 3
     2370189.544       592762.85     2370580.091      592641.946
     2370966.053      592496.803
#Sta/Elev= 30
       0 3193.12    38.9 3171.16    64.1 3154.93    71.3 3151.89   118.5 3125.17
     152  3104.8   172.9 3090.57   192.8 3079.07   244.5 3052.22  285.033028.974
     311 3014.03   336.2 2996.62   365.1 2993.85  385.332990.244   400.6 2978.43
   407.4 2976.31   415.9 2976.75   419.5  2978.5   425.7 2984.01   454.4 2999.01
   514.2 3037.79   527.1 3052.65   548.4 3067.64   578.3 3085.84   621.1 3108.95
   667.9 3136.48   705.2 3154.46   753.5 3179.97   787.7 3194.88   821.2 3211.17
#Mann= 5 ,-1 , 0
       0      .1       0  285.03     .06       0  385.33      .1       0
   400.6    .045       0   419.5      .1       0
Bank Sta=400.6,419.5
XS Rating Curve= 0 ,0
Exp/Cntr=0.3,0.1

Type RM Length L Ch R = 1 ,8111    ,271,267.9,264.9
XS GIS Cut Line= 3
      2370468.48      593177.894     2370752.708      592883.098
     2371036.935      592588.301
#Sta/Elev= 30
       0 3117.37    80.1 3075.16   137.5  3046.9   159.8 3039.34   187.7 3032.09
     228 3016.94   252.7 3009.59   293.1 2993.45     329 2980.42  339.852973.259
   343.3 2971.32   360.2 2971.96   383.6 2969.52   387.6 2968.44   399.8 2961.79
   412.4 2959.98   419.6 2960.59  421.98 2961.77   428.1 2968.56   433.7 2973.27
  463.942992.479   470.1 2995.99   518.6 3030.29   573.8 3065.94   597.8 3082.94
   620.9 3094.65     682 3128.63   709.8 3142.63   754.3 3162.96     819 3196.73
#Mann= 5 ,-1 , 0
       0      .1       0  339.85     .06       0   399.8    .045       0
  421.98     .06       0  463.94      .1       0
Bank Sta=399.8,421.98
XS Rating Curve= 0 ,0
Exp/Cntr=0.3,0.1

Type RM Length L Ch R = 1 ,7843    ,329.4,332.1,331.2
XS GIS Cut Line= 2
     2370734.145      593393.089     2371187.763      592705.287
#Sta/Elev= 30
       0 3153.79    44.7    3133   102.8 3091.76   126.2 3081.18   170.3 3055.85
  257.423012.836   291.7 2993.72     299 2987.79   313.5 2971.61   333.3 2955.35
   364.4 2955.05     386 2953.04  389.162951.693   399.7 2945.11   414.9 2943.87
   424.2 2945.29   435.1 2949.48   475.5 2982.59   492.9 2992.39   510.2 3003.79
   521.7  3012.8   531.5 3017.87   553.7 3032.11   582.4 3052.27   605.5  3065.7
   647.7 3092.87   697.4 3122.09     747 3147.97     793 3176.84   823.9 3193.69
#Mann= 5 ,-1 , 0
       0      .1       0  257.42     .06       0  389.16      .1       0
   399.7    .045       0   424.2      .1       0
Bank Sta=399.7,424.2
XS Rating Curve= 0 ,0
Exp/Cntr=0.3,0.1

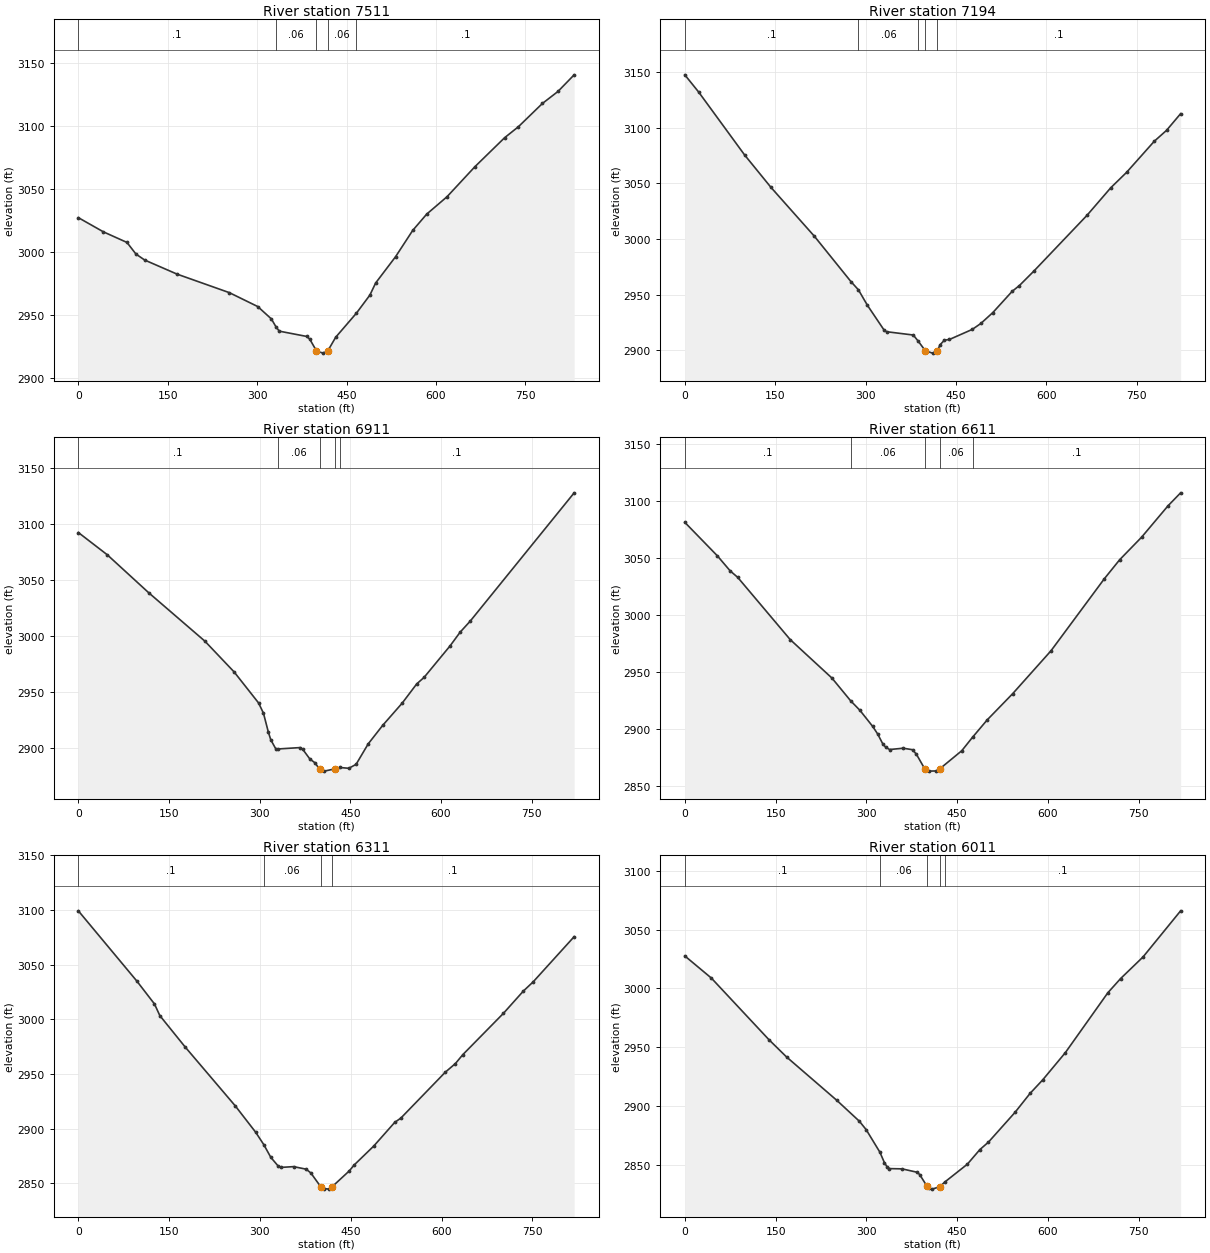
Type RM Length L Ch R = 1 ,7511    ,324.8,317.2,308.4
XS GIS Cut Line= 3
     2370957.944      593600.963     2371196.863      593271.732
     2371430.107      592916.604
#Sta/Elev= 30
       0 3027.41    42.2 3016.12    81.6 3007.75    96.6 2998.57   111.3  2993.8
   165.7 2982.62   253.4 2967.93     301 2956.91   323.8 2947.12  331.632940.773
   337.1 2937.42   383.1 2933.23   388.1 2931.16   399.32921.899   410.2    2920
  418.43 2921.76   431.7 2932.59   466.42951.651   489.1 2966.05   498.7 2975.59
   532.2 2996.48   560.9 3017.29   584.4 3030.22   618.4 3043.97   665.2 3067.79
   714.9 3090.71   738.1 3099.46   778.5 3117.96   804.5 3127.44   831.7 3140.64
#Mann= 5 ,-1 , 0
       0      .1       0  331.63     .06       0   399.3    .045       0
  418.43     .06       0   466.4      .1       0
Bank Sta=399.3,418.43
XS Rating Curve= 0 ,0
Exp/Cntr=0.3,0.1

Type RM Length L Ch R = 1 ,7194    ,281,282.8,283.8
XS GIS Cut Line= 2
     2371474.572      593765.752     2371512.504      592943.506
#Sta/Elev= 30
       0 3147.44    22.9 3132.04    99.4 3075.34     143 3046.31   215.1 3002.37
   275.7 2961.67   288.22954.228   303.2 2940.26   331.2 2917.73   335.2 2916.54
   379.3 2913.58  387.722907.897   399.3 2899.46   411.3 2897.31   419.3 2899.58
   423.9  2904.9     431 2908.96   439.3 2909.58   477.2 2918.63   491.4 2923.94
   511.4 2933.78   543.4 2952.81   555.5 2958.07   579.5 2971.05   667.6 3021.11
   707.2 3045.98   733.3 3059.73   779.4 3087.76   799.7 3097.52   823.1 3112.52
#Mann= 5 ,-1 , 0
       0      .1       0   288.2     .06       0  387.72      .1       0
   399.3    .045       0   419.3      .1       0
Bank Sta=399.3,419.3
XS Rating Curve= 0 ,0
Exp/Cntr=0.3,0.1

Type RM Length L Ch R = 1 ,6911    ,296.8,300,304.2
XS GIS Cut Line= 3
     2371717.964      593762.272     2371775.623      593355.068
      2371811.74      592947.477
#Sta/Elev= 30
       0 3092.15    47.9 3072.28   116.5 3038.43   209.4 2995.31   257.9  2967.8
   298.3 2940.19   306.4    2931   314.5  2914.1   318.5 2907.33   326.6 2899.43
  330.662899.187     367 2900.42     371 2899.13   383.2  2890.2   391.2 2887.01
   399.3 2881.23   407.1 2879.43   425.4 2881.55  432.282882.684   447.6 2881.96
   459.6 2885.46   479.7 2903.74   503.8 2920.32   535.8 2939.97     560  2957.2
   572.1 2962.96   615.1 2991.04   631.9 3003.35   648.4 3013.08   820.5 3127.52
#Mann= 5 ,-1 , 0
       0      .1       0  330.66     .06       0   399.3    .045       0
   425.4     .06       0  432.28      .1       0
Bank Sta=399.3,425.4
XS Rating Curve= 0 ,0
Exp/Cntr=0.3,0.1

Type RM Length L Ch R = 1 ,6611    ,300.3,300,299.7
XS GIS Cut Line= 3
     2371931.336      593837.914     2372058.216      593448.566
     2372185.095      593059.218
#Sta/Elev= 30
       0 3081.54    53.7 3052.16    74.9 3038.91    87.3 3033.25   174.1 2978.53
   243.1  2944.7  273.972924.738   289.3 2916.37   310.3  2902.3   318.7 2895.49
   327.1 2886.83   331.9 2883.94   338.3 2881.94   360.8  2883.1   376.3 2881.77
   382.7 2877.68  396.71 2864.64   402.8 2862.97   415.5 2863.13   420.8 2864.83
   457.5 2880.89  475.282892.722   499.6 2908.03   541.7 2931.07   604.9  2968.7
   693.1 3032.05   718.4 3048.72   754.5 3068.45   798.2 3096.06     819 3107.45
#Mann= 5 ,-1 , 0
       0      .1       0  273.97     .06       0  396.71    .045       0
   420.8     .06       0  475.28      .1       0
Bank Sta=396.71,420.8
XS Rating Curve= 0 ,0
Exp/Cntr=0.3,0.1

Type RM Length L Ch R = 1 ,6311    ,300.3,300,299.6
XS GIS Cut Line= 3
     2372223.628      593939.375     2372341.424      593547.184
      2372459.22      593154.992
#Sta/Elev= 30
       0 3099.28    96.6 3035.01   125.8 3014.01   134.6 3003.39   176.3 2974.75
   259.5 2920.56   292.9 2896.63  306.452885.169   317.9 2873.65   330.5  2865.4
   334.6 2864.42   355.5 2865.13   376.4 2862.79   384.1  2859.3   400.2 2846.87
   405.6 2845.07   413.9 2844.54  419.31 2846.79   447.4 2861.13   455.7 2866.69
   487.9 2883.93   522.6 2905.63   532.8 2909.59   606.1 2951.54   622.8 2959.46
   635.3 2967.77   702.2 3005.47   735.2  3025.9   751.3 3034.26     819 3075.63
#Mann= 4 ,-1 , 0
       0      .1       0  306.45     .06       0   400.2    .045       0
  419.31      .1       0
Bank Sta=400.2,419.31
XS Rating Curve= 0 ,0
Exp/Cntr=0.3,0.1

Type RM Length L Ch R = 1 ,6011    ,299.8,300,298.8
XS GIS Cut Line= 3
     2372525.074      594009.112      2372632.84      593614.047
     2372740.607      593218.981
#Sta/Elev= 30
       0 3027.62    43.8 3008.83   139.1 2956.37   168.1 2941.75   251.1 2904.89
   288.4 2887.11   299.6 2879.98  322.232860.851   329.8 2851.85     334 2848.48
   338.1 2846.88   358.9 2846.66   383.7 2843.79   387.9 2841.87   400.3 2831.73
   403.8 2829.98   408.6 2829.44   421.1 2831.49  429.072835.315   466.7 2850.62
   487.4 2863.04   501.6  2869.4   545.4 2894.64   570.3 2910.78   591.1 2922.23
   628.4  2945.3   698.9 2996.39   719.8 3008.34   756.9 3026.74     819 3065.94
#Mann= 5 ,-1 , 0
       0      .1       0  322.23     .06       0   400.3    .045       0
   421.1     .06       0  429.07      .1       0
Bank Sta=400.3,421.1
XS Rating Curve= 0 ,0
Exp/Cntr=0.3,0.1

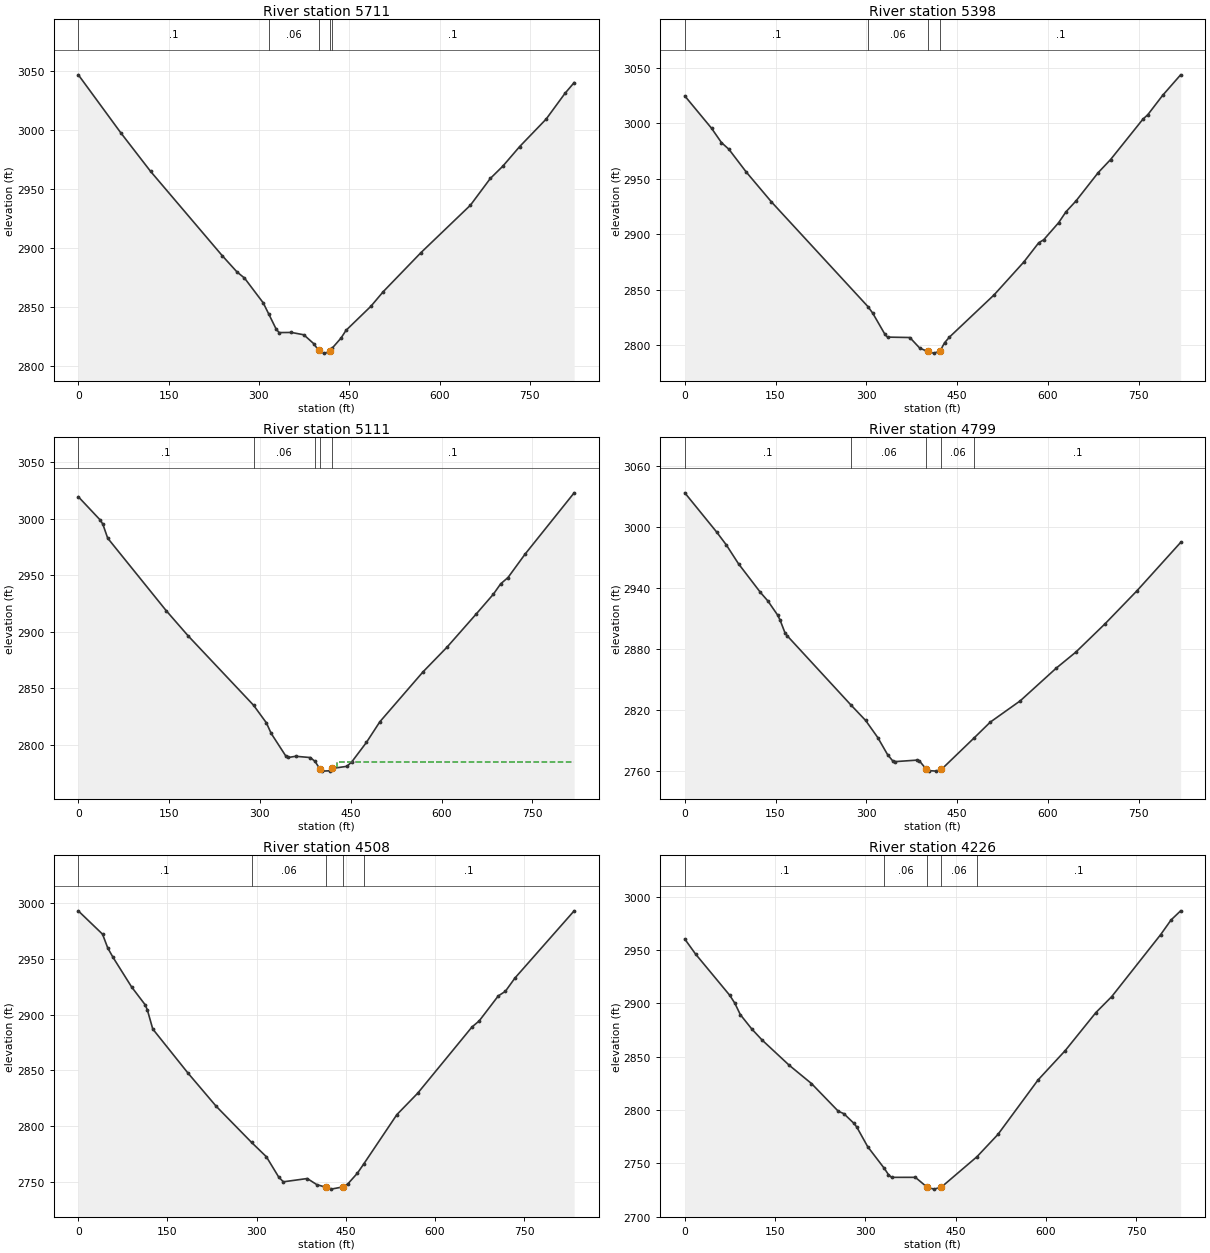
Type RM Length L Ch R = 1 ,5711    ,313,312.7,312.5
XS GIS Cut Line= 3
     2372829.387      594059.734     2372921.993      593660.338
     2373026.499      593260.148
#Sta/Elev= 30
       0 3046.87    70.7 2997.58   119.9 2965.06     239 2893.51   263.7 2879.61
     276 2874.52   307.1 2853.49   316.22844.114   328.5 2831.32   333.5 2828.27
     354 2828.38   374.5  2826.4   390.9 2818.92   399.2  2813.1   407.4 2810.84
   415.1 2811.49   418.3 2812.98  421.432814.912   436.3 2823.57   444.6 2830.13
   485.9 2850.54   506.6 2863.04   569.1 2896.07   651.3 2936.31   684.3 2958.96
     705 2969.34     733 2985.98   777.1 3009.35   808.4 3031.18   823.6  3040.3
#Mann= 5 ,-1 , 0
       0      .1       0   316.2     .06       0   399.2    .045       0
   418.3     .06       0  421.43      .1       0
Bank Sta=399.2,418.3
XS Rating Curve= 0 ,0
Exp/Cntr=0.3,0.1

Type RM Length L Ch R = 1 ,5398    ,288.5,287.3,285.7
XS GIS Cut Line= 2
     2373143.263      594098.051     2373319.906      593297.926
#Sta/Elev= 30
       0 3024.71    44.2 2995.57    60.6 2982.63    72.9 2976.61   101.5 2956.13
   143.1 2929.22  302.592834.797   310.5 2828.91   330.9 2809.62     335 2807.24
   371.9 2806.88   388.3 2797.31   401.5 2794.27   411.6  2792.8   421.7 2794.54
   429.3 2802.17   437.4 2807.27   511.2 2845.36   560.3 2874.99   584.9 2892.31
   593.1 2895.01   617.7 2910.35     630 2920.28   646.4 2929.96   683.2 2955.58
   703.7 2967.39     757  3003.7   765.2 3007.81   789.7 3025.24   819.4 3043.74
#Mann= 4 ,-1 , 0
       0      .1       0  302.59     .06       0   401.5    .045       0
   421.7      .1       0
Bank Sta=401.5,421.7
XS Rating Curve= 0 ,0
Exp/Cntr=0.3,0.1

Type RM Length L Ch R = 1 ,5111    ,311.3,312.2,311.9
XS GIS Cut Line= 3
     2373464.704      594143.052     2373515.706      593736.741
     2373566.708      593330.429
#Sta/Elev= 30
       0 3019.29    36.4  2998.6    40.5 2995.02    48.5 2982.72   145.2 2918.62
   181.6 2896.28  289.462835.104   310.6 2819.58   318.6 2810.17   342.8 2790.17
   346.9 2788.95     359 2790.02   383.1  2788.9  390.912785.541   398.9 2778.93
   403.3  2776.9   415.4 2777.22   419.4 2779.28   443.6 2781.14   451.7 2785.09
   475.9  2802.3   498.1 2820.54   569.5 2864.69   608.9 2886.36   657.3 2915.76
   685.5 2933.18   697.6 2942.36   709.7  2947.9   737.9 2968.59     819 3022.76
#Mann= 5 ,-1 , 0
       0      .1       0  289.46     .06       0  390.91      .1       0
   398.9    .045       0   419.4      .1       0
#XS Ineff= 2 , 0
                          427.46         2785.39
Permanent Ineff=
       F       F
Bank Sta=398.9,419.4
XS Rating Curve= 0 ,0
Exp/Cntr=0.3,0.1

Type RM Length L Ch R = 1 ,4799    ,291.4,290.8,289.4
XS GIS Cut Line= 2
     2373765.746      594178.797     2373880.851      593367.467
#Sta/Elev= 30
       0 3033.49    52.4  2995.1    68.6 2982.25    88.8 2963.64   125.1 2935.41
   137.3 2927.09   153.4 2913.21   157.5  2908.2   165.5 2895.88   169.6 2892.58
  274.152824.981   298.9 2809.47   318.9 2792.69   335.2  2775.8   343.3 2769.95
   347.3 2768.95   383.7 2770.44   387.8 2769.65   398.9 2761.64   404.1 2760.08
     416 2759.61   424.1 2761.26  478.022792.194   504.9 2807.84   554.3 2828.74
     614    2861   646.3 2876.74   694.8 2904.73   747.3 2937.07   819.5 2984.66
#Mann= 5 ,-1 , 0
       0      .1       0  274.15     .06       0   398.9    .045       0
   424.1     .06       0  478.02      .1       0
Bank Sta=398.9,424.1
XS Rating Curve= 0 ,0
Exp/Cntr=0.3,0.1

Type RM Length L Ch R = 1 ,4508    ,270.6,282.5,298.2
XS GIS Cut Line= 3
        2373961.      594207.5452374100.83134465593919.373754568
     2374147.693      593407.697
#Sta/Elev= 30
       0 2992.77    40.7 2971.95    49.6 2959.44    58.5 2951.05    89.6  2924.7
   112.6 2908.58   116.3 2903.78   125.2 2887.03   184.4 2847.59   231.9 2817.84
   291.42785.488   316.4 2772.59   337.2 2754.34   344.9 2750.19   385.1 2753.13
   401.1 2747.69     416 2745.39   425.2 2743.64   445.3 2745.63   453.3 2748.28
   469.4 2757.88  480.042766.107   535.9 2810.38   570.8 2829.48   662.2 2888.81
   674.3 2894.24   706.4 2916.63   718.4 2920.79   734.6 2932.73   834.1 2992.84
#Mann= 5 ,-1 , 0
       0      .1       0   291.4     .06       0     416    .045       0
   445.3     .06       0  480.04      .1       0
Bank Sta=416,445.3
XS Rating Curve= 0 ,0
Exp/Cntr=0.3,0.1

Type RM Length L Ch R = 1 ,4226    ,342.2,333.7,324.5
XS GIS Cut Line= 2
     2374032.398      594257.913     2374634.345      593695.623
#Sta/Elev= 30
       0 2960.32    17.9 2946.27    74.6 2907.65      83 2900.31    92.3 2889.42
   111.3 2876.01   128.3 2865.73   173.6 2841.95   210.4  2824.9     255 2798.91
   264.2 2796.64   281.1 2787.49   285.7 2784.08   303.8 2765.71  331.462745.311
   338.4 2739.44   343.4 2736.93     383 2736.94   402.8  2727.6   414.2 2725.88
   426.3 2727.81  485.282756.218   520.1  2777.1   586.8  2828.2   632.1 2855.84
     683 2891.46   709.3 2906.42   790.6 2964.55   807.8 2978.23   823.7  2986.8
#Mann= 5 ,-1 , 0
       0      .1       0  331.46     .06       0   402.8    .045       0
   426.3     .06       0  485.28      .1       0
Bank Sta=402.8,426.3
XS Rating Curve= 0 ,0
Exp/Cntr=0.3,0.1

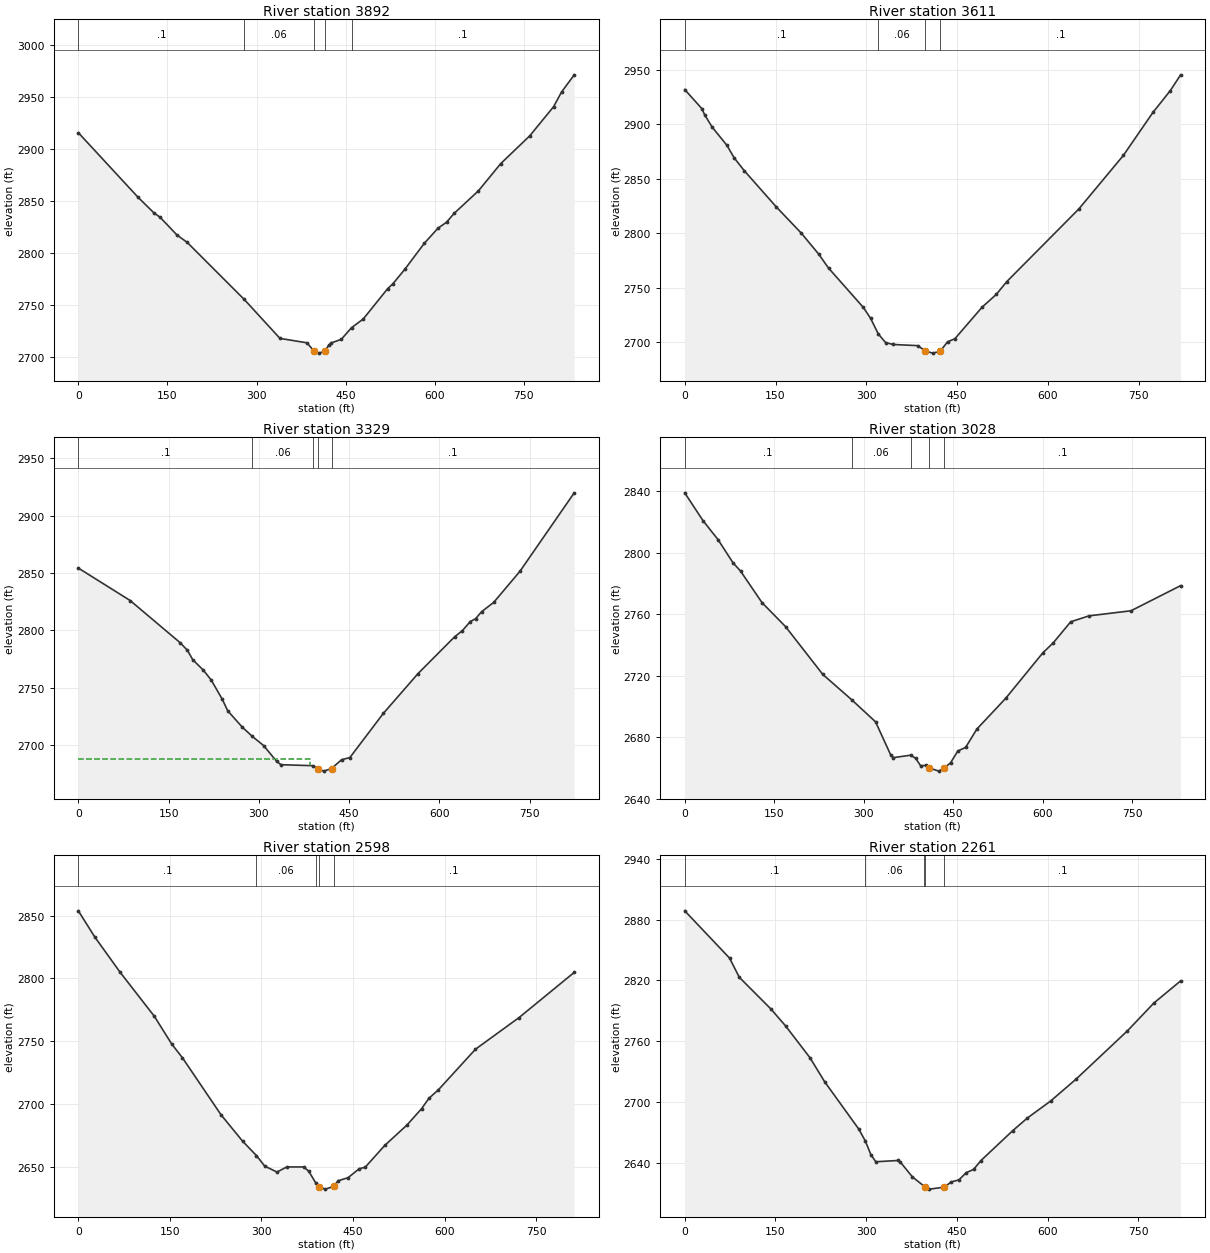
Type RM Length L Ch R = 1 ,3892    ,287.9,280.8,273.8
XS GIS Cut Line= 2
     2374505.951      594552.339      2374708.06      593742.278
#Sta/Elev= 30
       0 2915.64   100.4 2853.73   127.2 2838.68   137.5 2834.54   166.4 2817.21
   182.9 2810.53  279.372755.522   339.5 2718.13   384.9  2713.9  396.24 2706.37
   405.5 2703.99   415.4 2706.14     422 2711.93   426.1 2713.86   442.6 2717.17
  460.092728.471   479.7 2736.76   520.9 2765.96   529.2 2770.32   549.6 2784.41
   582.5 2809.44   605.6 2823.96   619.9 2829.66   632.6 2838.13   673.5 2859.75
   711.2 2885.99   760.1 2912.67   800.3 2940.72   813.5 2954.64   834.9 2971.21
#Mann= 5 ,-1 , 0
       0      .1       0  279.37     .06       0  396.24    .045       0
   415.4     .06       0  460.09      .1       0
Bank Sta=396.24,415.4
XS Rating Curve= 0 ,0
Exp/Cntr=0.3,0.1

Type RM Length L Ch R = 1 ,3611    ,284.6,281.6,278.3
XS GIS Cut Line= 3
     2374968.658      594542.797     2374880.552       594142.89
     2374795.545      593742.295
#Sta/Elev= 30
       0 2931.86    28.6 2914.14    32.7 2908.91    45.2 2897.47    69.5 2880.83
    81.8 2869.11    98.2 2857.52   151.5 2824.04   192.4 2800.25   221.1 2781.04
   237.5 2768.13   294.8 2732.16     307 2722.01  319.732707.673   331.7 2699.85
   343.9 2698.07   384.9    2697   397.6 2692.06   409.5 2690.13   421.8 2691.76
     434 2700.44   446.3 2703.41   491.3 2732.38   514.6    2744   531.7 2755.62
   650.8 2822.29   724.4 2871.43   773.4 2910.97     802  2930.9     819 2945.36
#Mann= 4 ,-1 , 0
       0      .1       0  319.73     .06       0   397.6    .045       0
   421.8      .1       0
Bank Sta=397.6,421.8
XS Rating Curve= 0 ,0
Exp/Cntr=0.3,0.1

Type RM Length L Ch R = 1 ,3329    ,299.3,301.9,302.2
XS GIS Cut Line= 2
     2375313.157      594450.103     2374990.523      593691.915
#Sta/Elev= 30
       0 2854.32    86.1    2826     169 2789.24   181.2 2782.59     190 2774.42
   207.8 2765.16   220.8 2756.59   239.1 2739.89   248.2 2729.76   272.6 2715.36
  289.292707.311   307.8 2699.41   329.5 2685.64   336.7 2682.68   389.92681.812
   397.7 2679.31   407.8 2677.07   420.8 2679.35   437.3    2687   451.2 2688.91
   506.7 2727.39   564.3 2762.13   625.1 2794.25   638.2  2799.7   651.2 2807.61
     660 2810.09   670.2 2816.28   690.1  2824.3   733.8  2851.5     824    2920
#Mann= 5 ,-1 , 0
       0      .1       0  289.29     .06       0   389.9      .1       0
   397.7    .045       0   420.8      .1       0
#XS Ineff= 2 , 0
          385.02 2687.37
Permanent Ineff=
       F       F
Bank Sta=397.7,420.8
XS Rating Curve= 0 ,0
Exp/Cntr=0.3,0.1

Type RM Length L Ch R = 1 ,3028    ,425.1,429.8,432.4
XS GIS Cut Line= 2
2375560.32078068594408.0130757182375309.64241253593615.169041775
#Sta/Elev= 30
       0 2838.85    30.5 2820.84    55.7 2808.52    80.9 2793.42    93.5 2788.06
   129.6 2767.51     169 2751.95   231.6 2720.84  280.032704.391     320 2690.06
   345.2 2668.73   349.4  2666.8   378.7  2668.4   387.1 2666.43   395.5 2661.55
   403.9 2661.75   410.3 2660.07   426.1 2658.05   434.9 2660.02   445.9 2663.54
   457.9 2671.14     471 2673.45   489.8 2685.35   538.2 2705.36   600.5 2734.91
   617.9 2741.39   647.2 2755.07   677.9 2758.92   748.3 2762.23   831.5 2778.56
#Mann= 5 ,-1 , 0
       0      .1       0  280.03     .06       0   378.7      .1       0
   410.3    .045       0   434.9      .1       0
Bank Sta=410.3,434.9
XS Rating Curve= 0 ,0
Exp/Cntr=0.3,0.1

Type RM Length L Ch R = 1 ,2598    ,337.1,336.7,335.2
XS GIS Cut Line= 2
2375891.42095817594371.0729383522375819.61016329593561.715239111
#Sta/Elev= 30
       0  2853.8    26.6 2833.24    68.4 2804.92   124.7 2769.73   152.8 2747.89
   170.5 2736.85   233.9 2691.35   269.2 2670.38  291.792658.956   305.4 2650.58
   325.5 2645.81   341.5  2649.9   369.6 2649.88   377.7 2646.35  389.532636.712
   393.7 2633.97   404.9 2632.23   418.1 2634.37   425.8 2638.89   441.9 2641.32
   460.2 2648.45     470 2649.67   502.1 2667.03   538.3 2683.18   562.4 2696.27
   574.4 2704.52     590 2711.32   650.7 2743.61   722.2 2768.85   812.5 2804.78
#Mann= 5 ,-1 , 0
       0      .1       0  291.79     .06       0  389.53      .1       0
   393.7    .045       0   418.1      .1       0
Bank Sta=393.7,418.1
XS Rating Curve= 0 ,0
Exp/Cntr=0.3,0.1

Type RM Length L Ch R = 1 ,2261    ,298.1,303.8,311.5
XS GIS Cut Line= 3
     2376238.165      594324.397     2376187.886      593917.535
     2376121.768      593513.104
#Sta/Elev= 30
       0 2888.87    74.1 2842.13    90.2 2823.15   142.6 2791.72   166.8 2775.01
   207.1 2743.57   231.3 2719.87   287.7 2673.08  298.442661.439   307.8 2647.67
   315.9 2640.76   352.2    2642   356.2 2640.65   376.3 2625.84  396.022616.461
   397.9 2615.55   404.6 2613.69   428.8 2615.62     441  2620.9   453.2 2622.79
   465.3 2629.94   477.5 2633.14   489.6 2641.89   542.3 2671.54   566.5 2684.02
   604.9 2700.82   646.7 2722.32   731.6 2770.04   775.5 2797.64   819.8 2819.61
#Mann= 5 ,-1 , 0
       0      .1       0  298.44     .06       0  396.02      .1       0
   397.9    .045       0   428.8      .1       0
Bank Sta=397.9,428.8
XS Rating Curve= 0 ,0
Exp/Cntr=0.3,0.1

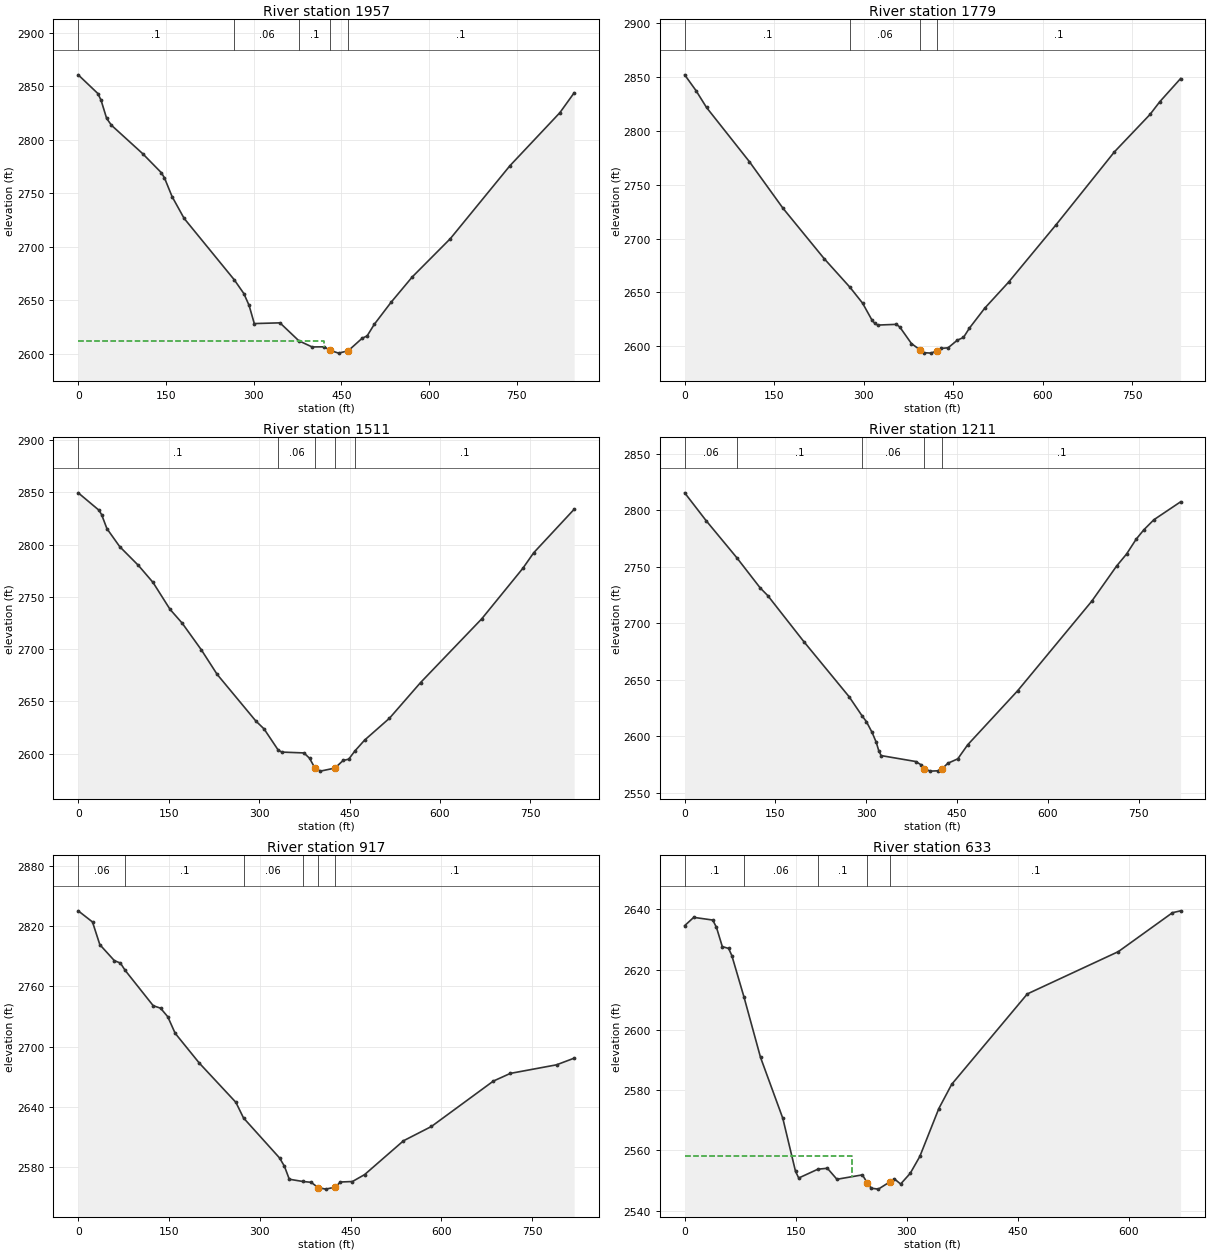
Type RM Length L Ch R = 1 ,1957    ,168.4,178.3,188.6
XS GIS Cut Line= 3
     2376324.959      594329.9972376465.24232276594039.525902032
     2376561.329      593522.884
#Sta/Elev= 30
       0 2860.55    33.6 2843.08      39 2836.92    48.6 2819.87    56.8 2813.45
   110.1 2786.95   142.1 2769.11   147.4 2764.37   160.5 2746.79   181.1  2726.4
  266.87 2668.99   283.3 2656.09   292.2 2645.09   301.1 2628.08     345 2628.76
  377.36 2611.98   399.9 2606.25   420.9 2606.35   430.8 2603.01   445.3 2600.46
   461.6  2602.6   485.6 2614.36   494.1 2616.57   506.2 2627.29   534.8 2647.83
   571.4 2671.76   636.4 2707.47   738.2 2775.55   823.7 2825.18   848.1 2843.74
#Mann= 5 ,-1 , 0
       0      .1       0  266.87     .06       0  377.36      .1       0
   430.8    .045       0   461.6      .1       0
#XS Ineff= 2 , 0
          419.75 2611.52
Permanent Ineff=
       F       F
Bank Sta=430.8,461.6
XS Rating Curve= 0 ,0
Exp/Cntr=0.3,0.1

Type RM Length L Ch R = 1 ,1779    ,269.3,267.9,264.1
XS GIS Cut Line= 2
     2376360.669      594351.484     2376879.959      593702.881
#Sta/Elev= 30
       0 2852.06      19  2837.4    36.6 2821.73   108.4 2771.42   164.7 2728.13
   233.7 2681.32  276.992654.679     298 2640.02   313.3 2624.75   318.5 2621.11
   323.6 2619.62   354.8 2620.29   360.5 2617.73   379.9 2602.47   394.6 2596.45
   400.4 2594.01   412.9 2593.56   423.1 2595.95   428.8 2597.89   441.4 2598.54
   456.8 2605.59   467.1 2608.11   477.1 2616.82   502.7 2635.29   542.6 2659.43
   622.3 2712.85   720.1 2780.58   779.6 2815.24   795.9 2827.01   830.9 2848.63
#Mann= 4 ,-1 , 0
       0      .1       0  276.99     .06       0   394.6    .045       0
   423.1      .1       0
Bank Sta=394.6,423.1
XS Rating Curve= 0 ,0
Exp/Cntr=0.3,0.1

Type RM Length L Ch R = 1 ,1511    ,307.4,300,293.6
XS GIS Cut Line= 3
     2376626.119      594511.935     2376843.353      594165.691
     2377044.962      593804.375
#Sta/Elev= 30
       0  2849.6    34.3 2833.02    38.8 2828.77    47.6 2815.34    68.9 2798.06
    99.9  2780.1     124  2763.9   152.3 2738.09   172.4 2724.91   204.3 2699.27
   230.4 2675.88   294.7 2631.16   308.2 2623.69  331.772603.329   337.8 2601.49
   374.3 2600.69   383.7 2595.58   392.6 2586.15   401.6 2583.27   425.7 2586.18
   439.4 2593.49   448.6 2594.69  458.722602.465     475 2612.96   516.2 2633.88
   567.7 2667.98   669.1 2728.93   737.2 2777.21   755.5 2792.31   822.5 2833.86
#Mann= 5 ,-1 , 0
       0      .1       0  331.77     .06       0   392.6    .045       0
   425.7     .06       0  458.72      .1       0
Bank Sta=392.6,425.7
XS Rating Curve= 0 ,0
Exp/Cntr=0.3,0.1

Type RM Length L Ch R = 1 ,1211    ,298.8,293.9,287.6
XS GIS Cut Line= 3
     2377047.052      594669.581     2377124.425      594267.501
     2377214.424      593867.763
#Sta/Elev= 30
       0 2815.44    35.3 2790.89   85.982758.086   124.9 2731.16   137.2  2724.5
   196.7 2683.82   271.6 2634.97   293.22617.897   300.1 2612.95   309.5 2603.43
   316.4 2594.66   320.5 2587.33   324.5 2582.84   381.6  2577.6   389.7 2574.94
   394.9 2571.26     406 2569.08   418.3 2569.37   425.3 2571.25   434.7 2576.03
   451.1 2579.95   467.5  2592.4   550.1 2640.29   672.5 2719.56   713.5 2750.66
   729.9 2761.26   745.8 2774.43   758.6 2782.79     775  2791.6   819.2 2807.49
#Mann= 5 ,-1 , 0
       0     .06       0   85.98      .1       0   293.2     .06       0
   394.9    .045       0   425.3      .1       0
Bank Sta=394.9,425.3
XS Rating Curve= 0 ,0
Exp/Cntr=0.3,0.1

Type RM Length L Ch R = 1 ,917     ,289.6,284.2,278
XS GIS Cut Line= 2
     2377446.057       594702.46     2377382.497       593885.84
#Sta/Elev= 30
       0 2835.61    23.6 2824.48    35.7 2801.81    59.7 2785.86    69.7 2783.42
   77.412776.231   123.9  2740.8     136 2738.34   147.9  2729.8   160.1 2713.29
     200 2683.48   260.4 2644.27  273.04 2628.65   332.6 2588.65   340.6  2580.4
   348.6 2567.44  370.852565.193   384.7 2564.35   396.2 2559.08   408.8 2557.54
   424.9 2559.61   432.9 2564.65   452.9 2565.14     473 2572.05   537.2 2605.84
   583.4 2620.14   685.6 2665.48   713.7 2673.17     790 2681.74   819.1 2688.39
#Mann= 6 ,-1 , 0
       0     .06       0   77.41      .1       0  273.04     .06       0
  370.85      .1       0   396.2    .045       0   424.9      .1       0
Bank Sta=396.2,424.9
XS Rating Curve= 0 ,0
Exp/Cntr=0.3,0.1

Type RM Length L Ch R = 1 ,633     ,311.6,328.5,344.9
XS GIS Cut Line= 3
 2377779.0464435594454.1973227692377623.66764397594059.538070445
      2377492.92      593851.724
#Sta/Elev= 30
       0 2634.61    12.2 2637.36    37.9 2636.47    42.9 2634.05    50.8 2627.67
    59.4 2627.03    63.7 2624.65   80.012610.999   102.4  2590.9   132.5 2570.67
   149.7 2553.03     154 2550.85  179.972553.781   192.7 2554.08   205.6 2550.43
     240 2551.89   246.4 2549.31     252 2547.46   261.5 2547.16   277.3  2549.6
     283  2550.6   291.6 2548.85   304.5 2552.38   317.5 2557.99   343.2 2573.91
   360.6 2581.96   462.7 2611.95   585.6 2625.99   658.7 2638.91   669.7 2639.53
#Mann= 5 ,-1 , 0
       0      .1       0   80.01     .06       0  179.97      .1       0
   246.4    .045       0   277.3      .1       0
#XS Ineff= 2 , 0
          225.94 2558.31
Permanent Ineff=
       F       F
Bank Sta=246.4,277.3
XS Rating Curve= 0 ,0
Exp/Cntr=0.3,0.1

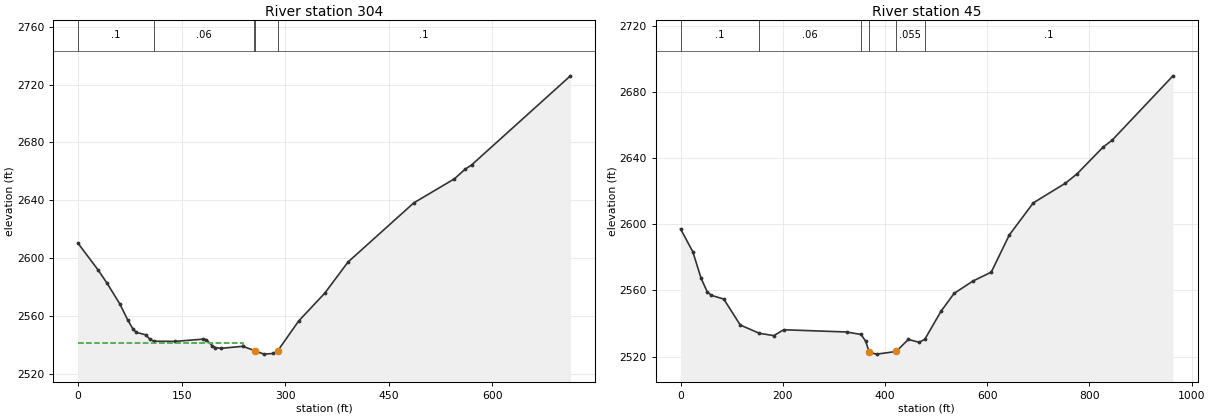
Type RM Length L Ch R = 1 ,304     ,249.2,259.1,266.6
XS GIS Cut Line= 4
2377812.10145176594415.9130629722377950.63967698594325.372333103
2378044.45296335 594120.292125692377856.82639061593858.487605587
#Sta/Elev= 30
       0 2610.25    28.7    2592    41.4 2583.03    60.5  2568.3      72 2557.11
    79.6 2550.87    84.4 2548.56      98 2546.86   104.2  2543.8  109.992542.419
   140.8 2542.32   181.4 2543.89   185.8 2543.55   194.6 2539.22     199 2538.06
   206.7 2537.48   238.6 2538.93  254.942536.054   256.2  2535.7   269.4  2533.5
   282.6 2533.96  289.25 2535.82   319.6 2556.48   357.4 2575.73     391 2597.25
   486.2 2638.17   545.2 2654.87   560.1 2661.32   569.9  2664.4   713.1 2726.13
#Mann= 5 ,-1 , 0
       0      .1       0  109.99     .06       0  254.94      .1       0
   256.2    .045       0  289.25      .1       0
#XS Ineff= 2 , 0
          238.95  2541.4
Permanent Ineff=
       F       F
Bank Sta=256.2,289.25
XS Rating Curve= 0 ,0
Exp/Cntr(USF)=0,0
Exp/Cntr=0.3,0.1

Type RM Length L Ch R = 1 ,45      ,,,
XS GIS Cut Line= 4
2377835.00934727594436.639254146 2378187.9058938594388.419282125
2378289.06177319594279.8144664952377976.82012899593943.574074621
#Sta/Elev= 30
       0 2597.17      24 2583.32    40.1 2567.36    52.2 2559.13    60.3 2557.03
    84.5 2554.78   116.8 2539.08  154.312534.085   182.5 2532.68   201.6 2536.24
     325 2534.88  353.012533.377   362.1 2529.37   369.2 2522.51   383.8  2521.5
   421.5 2523.09   445.7 2530.36   466.8 2528.67   477.92530.485   509.7 2547.48
   535.2 2558.22     572 2565.67   607.9 2571.08   643.2 2593.55   690.2 2612.95
   753.1 2624.85   775.8  2630.5   826.7 2646.65   844.3 2650.81963.4523 2689.75
#Mann= 6 ,-1 , 0
       0      .1       0  154.31     .06       0  353.01    .055       0
   369.2    .045       0   421.5    .055       0   477.9      .1       0
Bank Sta=369.2,421.5
XS Rating Curve= 0 ,0
Exp/Cntr(USF)=0,0
Exp/Cntr=0.3,0.1
LCMann Table=0

Chan Stop Cuts=-1
Use User Specified Reach Order=0
Composite Channel Slope=5